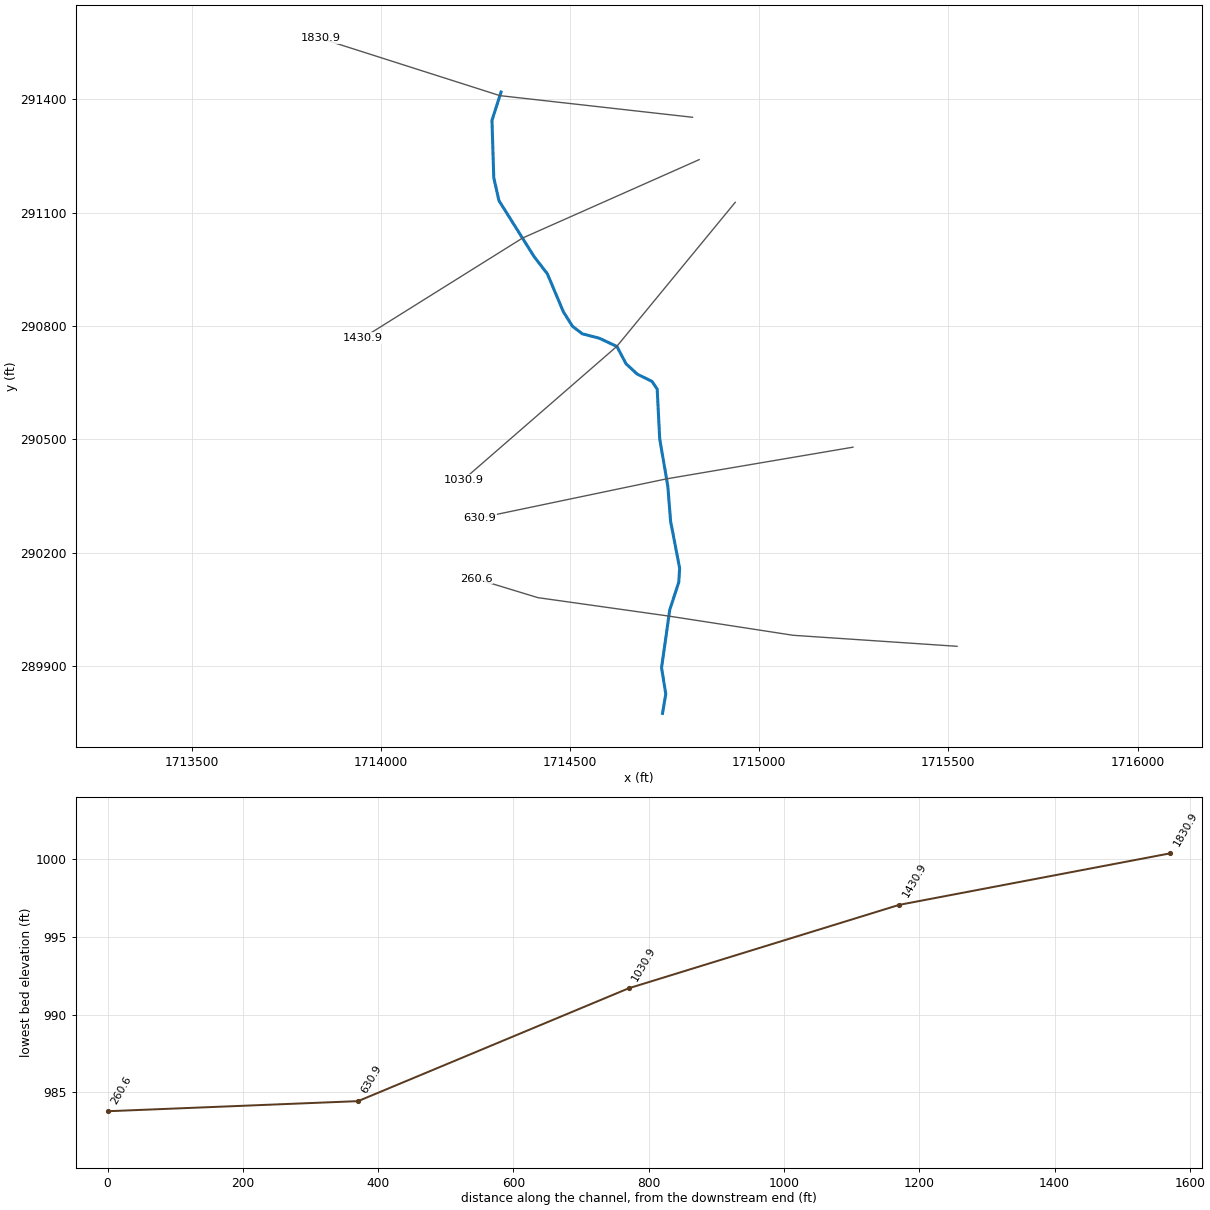
--- JohnsonFk.prj (project) ---

Proj Title=JohnsonFk
Current Plan=p01
Default Exp/Contr=0,0
English Units
Geom File=g01
Flow File=f01
Plan File=p01
BEGIN DESCRIPTION:
END DESCRIPTION:
DSS Export Rating Curves= 0
DSS Export Rating Curve Sorted= 0
DSS Export Volume Flow Curves= 0
DXF OffsetX= 0
DXF OffsetY= 0
DXF ScaleX= 0
DXF ScaleY= 0

--- JohnsonFk.p01 (plan) ---

Plan Title=Floodplain
Program Version=4.00
Geom File=g01
Flow File=f01
K Sum by GR=0
Std Step Tol=0.01
Critical Tol=0.01
Num of Std Step Trials=20
Max Error Tol=0.3
Flow Tol Ratio=0.001
Split Flow NTrial=30
Split Flow Tol=0.02
Split Flow Ratio=0.02
Log Output Level=0
Friction Slope Method=1
Unsteady Friction Slope Method=2
Unsteady Bridges Friction Slope Method=1
Global Log Level=0
CheckData=False
Run HTab=0
Run UNet=0
Run PostProcess=0
UNET Theta=0
UNET Theta Warmup=0
UNET ZTol=0
UNET ZSATol=0
UNET MxIter=0
UNET MaxInSteps=0
UNET DtIC=0
UNET DtMin=0
UNET MaxCRTS=0
UNET WFStab=0
UNET SFStab=0
UNET WFX=0
UNET SFX=0
UNET DSS MLevel=0
UNET DZMax Abort=0
UNET Convert EG Bridges=0
UNET Use Existing IB Tables=0
UNET Froude Limit=0
UNET Froude Power=0
Write IC File=0
Echo Input=False
Echo Output=False
Write Detailed=0

--- JohnsonFk.f01 (steady flow) ---

Flow Title=NFF Regression Equation
Program Version=4.00
Number of Profiles= 1
Profile Names=P100yr
River Rch & RM=JohnsonFk,Main            ,1830.9
730.5429
River Rch & RM=JohnsonFk,Main            ,260.6
759.9212
Boundary for River Rch & Prof#=JohnsonFk,Main            , 1
Up Type= 0
Dn Type= 3
Dn Slope=0.0113
DSS Import GetInterval= 0
DSS Import GetPeak= 0
DSS Import FillOption= 0

--- JohnsonFk.g01 (geometry) ---

Geom Title=USGS 3m DEM
Program Version=4.00

River Reach=JohnsonFk     ,Main
Reach XY= 25
     1714317.266      291419.672     1714293.268      291344.590
     1714298.034      291192.551     1714300.457      291181.883
     1714311.755      291132.098     1714404.507      290984.059
     1714439.624      290938.428     1714482.199      290837.430
     1714506.022      290799.463     1714532.003      290779.478
     1714577.246      290767.653     1714623.728      290745.758
     1714647.551      290700.245     1714677.324      290672.655
     1714716.278      290653.359     1714730.084      290633.090
     1714736.699      290501.681     1714758.222      290375.230
     1714765.534      290283.070     1714789.438      290158.754
     1714787.220      290121.986     1714763.210      290048.062
     1714741.599      289894.868     1714752.823      289825.563
     1714744.151      289774.255

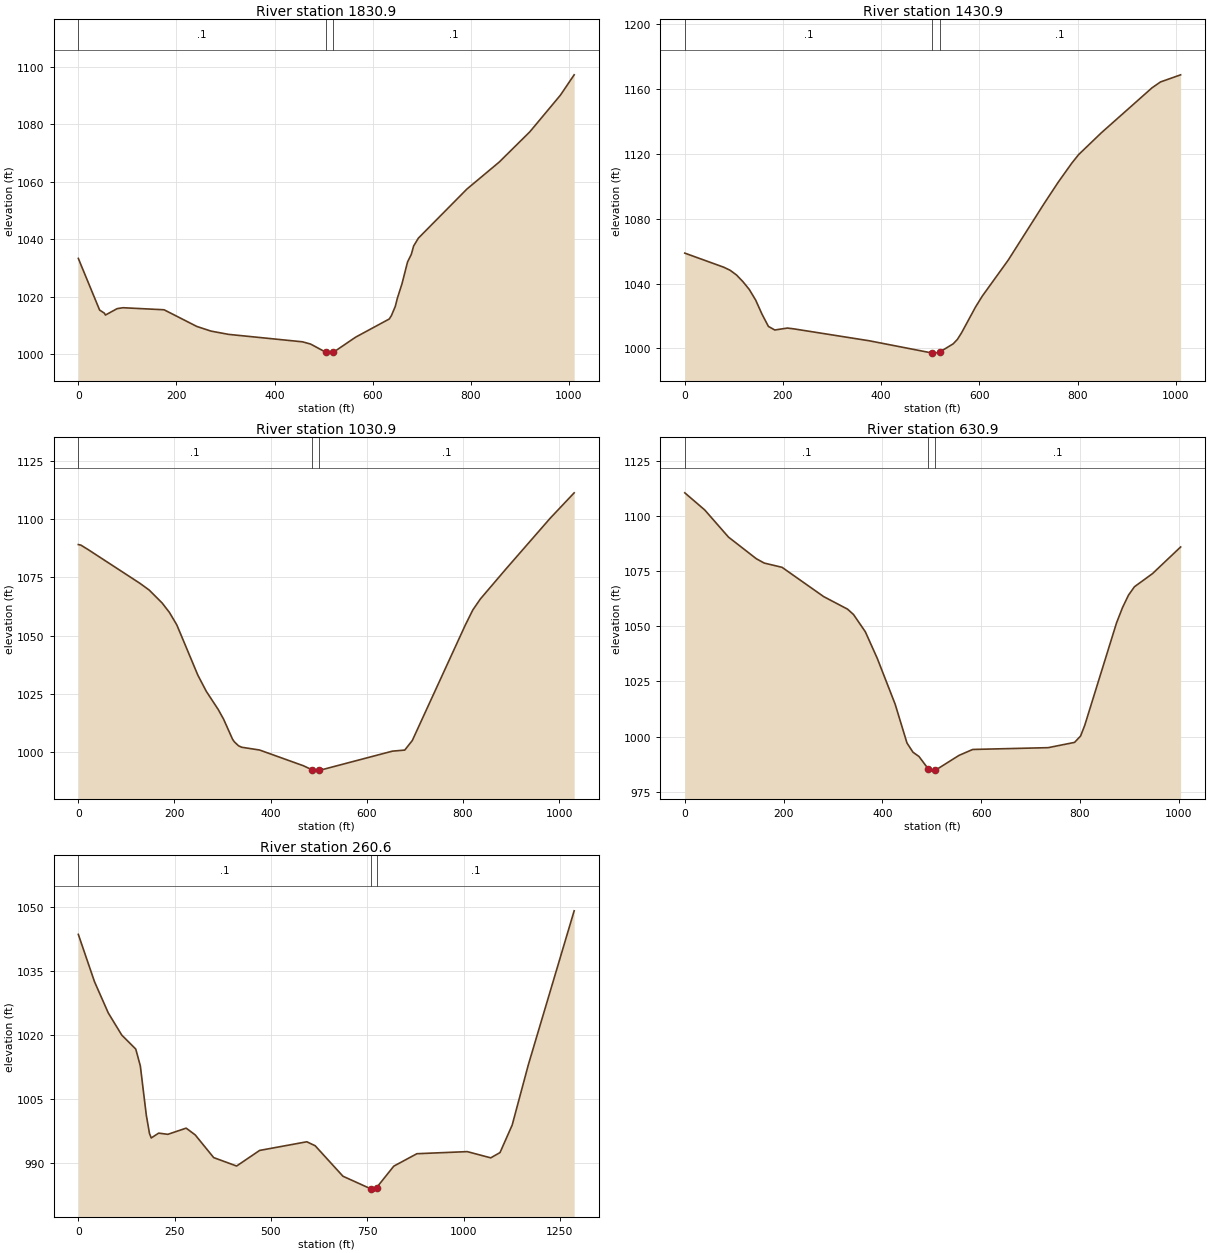
Type RM Length L Ch R = 1 ,1830.9,387.982,400,419.715
XS GIS Cut Line= 3
     1714823.527      291352.820     1714314.222      291410.146
     1713839.503      291561.881
#Sta/Elev= 30
       0 1033.33    43.4 1015.36    53.0 1014.29    55.3 1013.63    79.2 1015.86
    91.2 1016.17   174.8 1015.46   241.5 1009.66   270.4 1008.04   306.2 1006.90
   456.9 1004.31   473.5 1003.53     505 1000.64   509.3 1000.37     520 1000.67
   565.4 1005.93   633.9 1012.25   638.3 1013.43   646.3 1016.67   650.4 1019.45
   659.9 1024.52   671.2 1032.10   678.8 1034.71   683.7 1037.68   693.3 1040.39
   792.1 1057.45   858.2 1066.88   920.5 1077.39   982.9 1090.16  1010.9 1097.23
#Mann= 3 , 0 , 0
       0     0.1       0     505   0.045       0     520     0.1       0
Bank Sta=     505,     520
Exp/Cntr=0.3,0.1

Type RM Length L Ch R = 1 ,1430.9,389.457,400,403.124
XS GIS Cut Line= 3
     1714841.063      291240.652     1714373.913      291032.890
     1713951.393      290768.166
#Sta/Elev= 30
       0 1058.80    79.4 1050.09    92.4 1048.20   105.4 1045.28   118.4 1041.19
   131.4 1036.34   144.3 1029.85   157.3 1021.09   170.3 1013.55   183.3 1011.34
   209.3 1012.54   222.3 1012.03   375.6 1004.69   503.8  997.13   508.2  997.06
   518.8  997.67   546.7 1002.80   555.4 1005.59   564.0 1009.77   592.0 1025.45
   606.0 1032.30   658.7 1054.46   732.1 1089.50   760.1 1102.38   788.1 1114.29
   802.2 1119.63   848.2 1133.02   951.6 1160.84   968.8 1164.46  1009.9 1168.87
#Mann= 3 , 0 , 0
       0     0.1       0   503.8   0.045       0   518.8     0.1       0
Bank Sta=   503.8,   518.8
Exp/Cntr=0.3,0.1

Type RM Length L Ch R = 1 ,1030.9,416.959,400,388.114
XS GIS Cut Line= 3
     1714936.460      291127.666     1714623.229      290745.993
     1714217.763      290392.989
#Sta/Elev= 30
       0 1089.14     5.2 1088.92    20.6 1086.96   128.1 1072.48   147.5 1069.56
   174.2 1064.04   189.5 1059.95   204.9 1054.57   248.7 1032.93   266.3 1025.97
   290.9 1018.23   302.1 1014.06   320.8 1005.40   324.6 1004.27   333.1 1002.61
   339.6 1001.97   377.0 1000.77   468.1  994.01   486.2  992.24   493.4  991.69
   501.2  992.00   653.2 1000.28   678.9 1000.74   694.6 1004.84   804.8 1054.48
   820.6 1061.05   836.3 1065.76   888.9 1078.52   981.4 1100.46  1031.3 1111.40
#Mann= 3 , 0 , 0
       0     0.1       0   486.2   0.045       0   501.2     0.1       0
Bank Sta=   486.2,   501.2
Exp/Cntr=0.3,0.1

Type RM Length L Ch R = 1 ,630.9,377.635,370.341,362.453
XS GIS Cut Line= 3
     1715247.618      290479.176     1714754.806      290395.296
     1714261.610      290291.976
#Sta/Elev= 30
       0 1110.40    40.4 1102.64    88.5 1090.35   144.8 1080.57   160.8 1078.61
   196.9 1076.68   281.2 1063.42   329.4 1057.76   341.5 1055.34   365.5 1047.51
   389.6 1035.51   425.8 1014.78   449.8  997.18   461.9  993.00   474.1  991.06
   492.4  985.60   498.0  984.43   507.4  984.84   555.0  991.54   582.9  994.24
   735.6  995.05   789.1  997.44   801.3 1000.34   809.7 1005.17   874.0 1051.51
   886.2 1058.49   898.3 1064.10   910.4 1067.90   946.8 1073.82  1003.8 1085.89
#Mann= 3 , 0 , 0
       0     0.1       0   492.4   0.045       0   507.4     0.1       0
Bank Sta=   492.4,   507.4
Exp/Cntr=0.3,0.1

Type RM Length L Ch R = 1 ,260.6,260.903,260.571,259.98
XS GIS Cut Line= 5
     1715522.810      289951.876     1715089.628      289981.028
     1714757.979      290032.294     1714414.509      290080.749
     1714251.272      290130.595
#Sta/Elev= 30
       0 1043.55    42.0 1032.45    77.7 1025.13   112.7 1019.93   149.1 1016.64
   161.0 1012.68   176.5 1001.12   184.8  996.81   189.3  995.79   208.6  996.92
   232.4  996.64   280.0  998.09   303.5  996.50   351.4  991.18   410.9  989.20
   470.7  992.86   593.2  994.89   614.9  993.96   687.0  986.81   759.3  983.85
   771.1  983.78   774.3  984.12   819.0  989.17   879.0  992.09  1009.7  992.58
  1070.8  991.12  1094.8  992.36  1126.3  998.79  1168.5 1013.01  1287.3 1049.08
#Mann= 3 , 0 , 0
       0     0.1       0   759.3   0.045       0   774.3     0.1       0
Bank Sta=   759.3,   774.3
Exp/Cntr=0.3,0.1